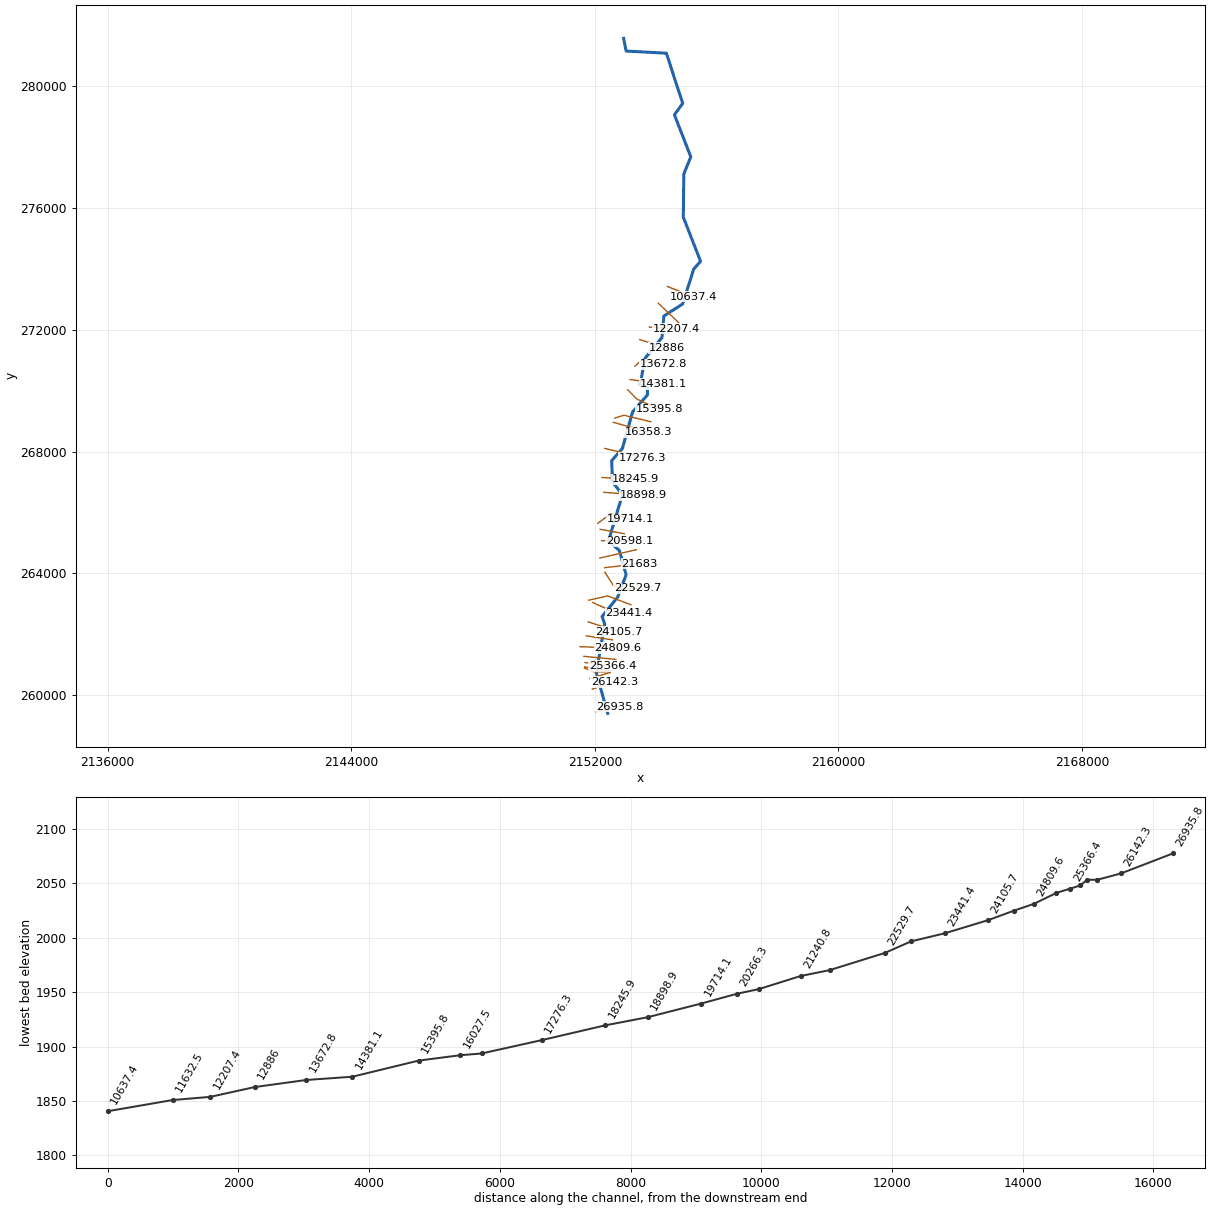
--- HartsRun.prj (project) ---

Proj Title=HartsRun
Current Plan=p01
Geom File=g01
Flow File=f01
Plan File=p01
DSS Export Rating Curves=0
DSS Export Rating Curve Sorted=0
DSS Export Volume Flow Curves=0
DXF OffsetX=0
DXF OffsetY=0
DXF ScaleX=0
DXF ScaleY=0

--- HartsRun.p01 (plan) ---

Plan Title=Floodplain
Program Version=4.00
Geom File=g01
Flow File=f01
K Sum by GR=0
Std Step Tol=0.01
Critical Tol=0.01
Num of Std Step Trials=20
Max Error Tol=0.3
Flow Tol Ratio=0.001
Split Flow NTrial=30
Split Flow Tol=0.02
Split Flow Ratio=0.02
Log Output Level=0
Friction Slope Method=1
Unsteady Friction Slope Method=2
Unsteady Bridges Friction Slope Method=1
Global Log Level=0
CheckData=False
Run HTab=0
Run UNet=0
Run PostProcess=0
UNET Theta=0
UNET Theta Warmup=0
UNET ZTol=0
UNET ZSATol=0
UNET MxIter=0
UNET MaxInSteps=0
UNET DtIC=0
UNET DtMin=0
UNET MaxCRTS=0
UNET WFStab=0
UNET SFStab=0
UNET WFX=0
UNET SFX=0
UNET DSS MLevel=0
UNET DZMax Abort=0
UNET Convert EG Bridges=0
UNET Use Existing IB Tables=0
UNET Froude Limit=0
UNET Froude Power=0
Write IC File=0
Echo Input=False
Echo Output=False
Write Detailed=0

--- HartsRun.f01 (steady flow) ---

Flow Title=NFF Regression Equation
Program Version=4.00
Number of Profiles=1
Profile Names=P100yr
River Rch & RM=HartsRun,Main      ,26935.8
533.5893
River Rch & RM=HartsRun,Main      ,25780.1
584.3071
River Rch & RM=HartsRun,Main      ,22928.8
647.6691
River Rch & RM=HartsRun,Main      ,22529.7
720.9590
River Rch & RM=HartsRun,Main      ,21683
989.2965
River Rch & RM=HartsRun,Main      ,20598.1
1034.766
River Rch & RM=HartsRun,Main      ,18245.9
1114.020
River Rch & RM=HartsRun,Main      ,16027.5
1235.337
River Rch & RM=HartsRun,Main      ,15395.8
1411.972
River Rch & RM=HartsRun,Main      ,12886
1528.262
River Rch & RM=HartsRun,Main      ,11632.5
1640.828
River Rch & RM=HartsRun,Main      ,8552.2
1804.659
River Rch & RM=HartsRun,Main      ,6713.9
1936.648
River Rch & RM=HartsRun,Main      ,1772.1
2143.602
Boundary for River Rch & Prof#=HartsRun,Main      ,1
Up Type=0
Dn Type=3
Dn Slope=0.023755

--- HartsRun.g01 (geometry) ---

Geom Title=USGS 10m DEM
Program Version=4.00

River Reach=HartsRun        ,Main
Reach XY= 30
     2152422.939      259405.069      2152048.68      260728.142
     2152324.162      262335.878     2152236.662      262582.753
     2152755.412      263228.065     2153027.287       263956.19
     2152805.412       264756.19     2152444.475      265051.503
     2152905.115      266584.227      2152578.85      267001.503
      2152553.85      267701.503     2152905.412      268101.503
     2153237.212      269296.421     2153727.287      269859.315
     2153727.287      270114.003     2153489.787      270195.253
     2153646.037       271056.19     2154205.412      271745.253
     2154267.912       272449.94     2154881.975      272842.128
       2155247.6       273987.44       2155472.6      274245.253
     2154905.412      275695.253       2154922.6       277112.44
     2155152.287       277674.94     2154613.615      279055.214
     2154886.532      279430.539     2154349.032      281075.852
     2153028.719      281146.164     2152946.007      281563.907

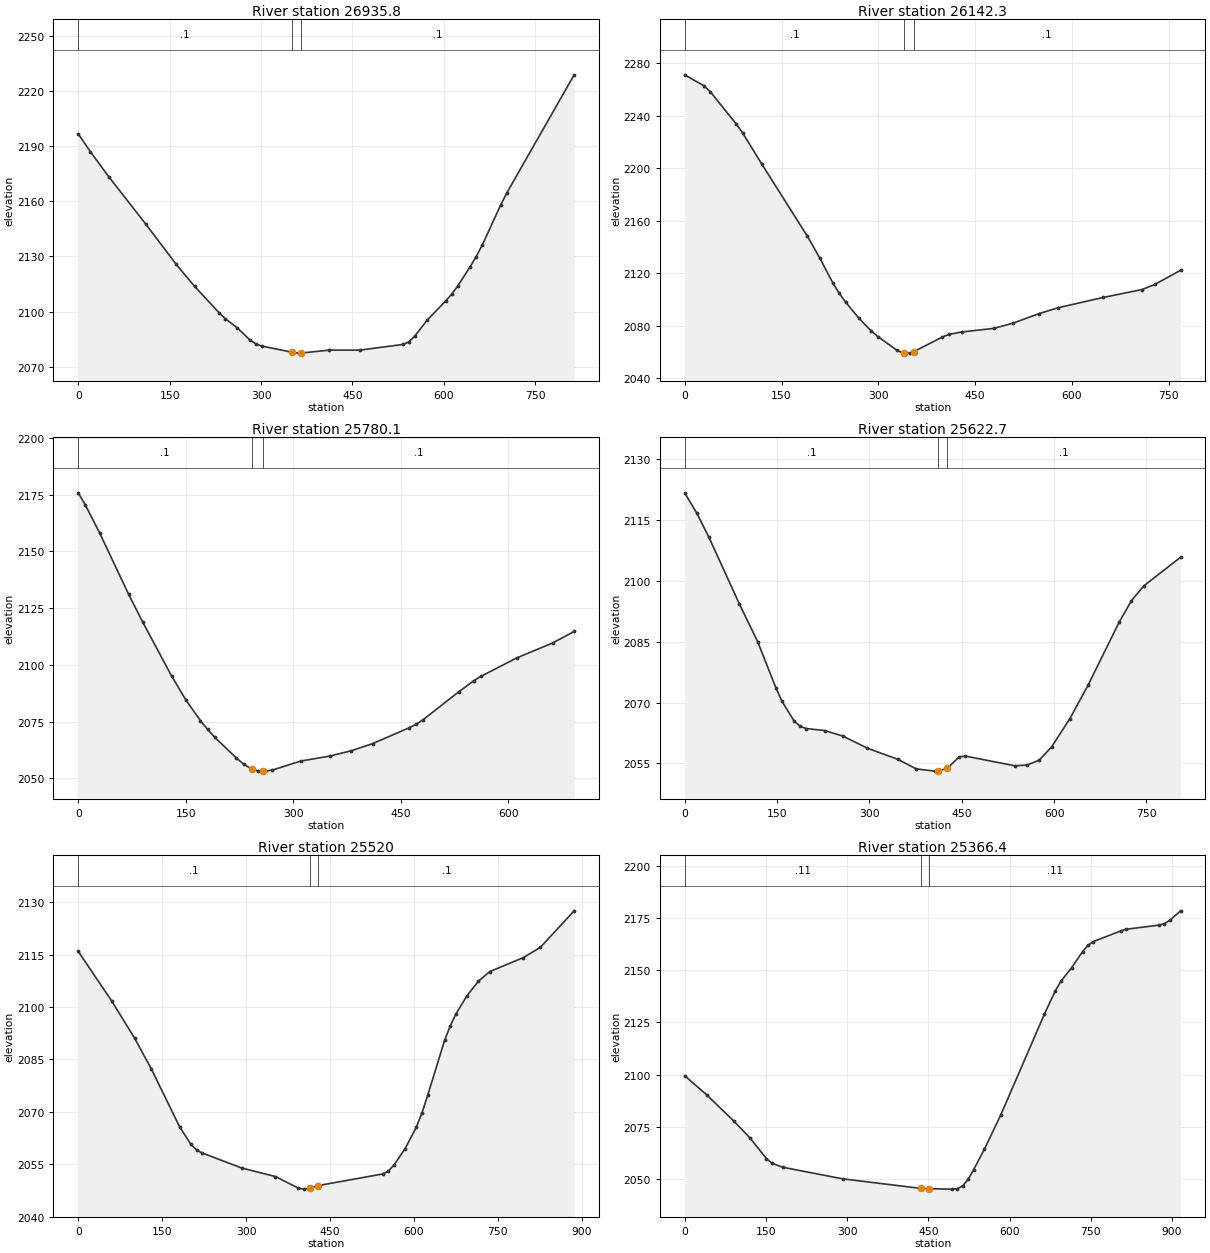
Type RM Length L Ch R = 1 ,26935.8 ,790.7,793.5,796.2
XS GIS Cut Line= 2
     2152018.213      259459.955     2152816.559      259617.167
#Sta/Elev= 30
       0 2196.83    20.1 2187.06    50.2 2173.43   110.5 2147.82   160.7 2125.76
   190.9 2113.72     231 2099.39   241.1 2096.15   261.2 2091.08   281.3 2084.61
   291.3 2082.34   301.4 2081.17   350.5 2077.84   361.6 2077.32   365.5 2077.37
   411.9 2078.95   462.1 2078.96   532.4 2082.03   542.4 2083.41   552.5  2086.7
   572.6 2095.34   602.7 2105.68   612.8 2109.51   622.8 2113.98   642.9 2124.31
     653 2129.96     663 2136.29   693.1 2158.02   703.2 2164.65   813.7 2229.01
#Mann= 3 , 0 , 0
       0      .1       0   350.5    .045       0   365.5      .1       0
Bank Sta=350.5,365.5
XS Rating Curve= 0 ,0
Exp/Cntr=0.3,0.1

Type RM Length L Ch R = 1 ,26142.3 ,362.6,362.2,361.9
XS GIS Cut Line= 2
     2151915.042      260201.803     2152647.064      260435.166
#Sta/Elev= 30
       0 2271.15    29.9 2262.79    39.9 2258.12    79.8 2233.76    89.8 2226.84
   119.7  2202.9   189.6 2148.49   209.5 2131.31   229.5 2112.49   239.5 2104.53
   249.4 2097.78   269.4 2085.88   289.4 2075.63   299.4 2071.56   329.3 2060.96
   339.3 2058.94   339.5 2058.94   349.2 2059.04   354.5    2060   399.1 2071.15
   409.1 2073.18   429.1 2075.09     479  2077.8   508.9 2081.84   548.8 2089.06
   578.7 2093.57   648.6 2101.42   708.4  2107.4   728.4 2111.34   768.3 2122.13
#Mann= 3 , 0 , 0
       0      .1       0   339.5    .045       0   354.5      .1       0
Bank Sta=339.5,354.5
XS Rating Curve= 0 ,0
Exp/Cntr=0.3,0.1

Type RM Length L Ch R = 1 ,25780.1 ,163.9,157.4,150.8
XS GIS Cut Line= 2
     2151836.435      260548.162     2152499.677      260744.678
#Sta/Elev= 30
       0  2175.8      10 2170.42    30.1 2157.97    70.2 2131.16    90.2 2118.69
   130.3 2095.05   150.4 2084.38   170.4 2075.44   180.4 2071.54   190.5 2068.02
   220.6 2058.94   230.6 2056.26   242.1 2053.98   250.6 2053.17   257.1 2053.15
   260.7 2053.14   270.7  2053.6   310.8 2057.61   350.9 2059.78     381 2062.14
     411 2065.31   461.2 2072.19   471.2 2073.76   481.2 2075.84   531.3 2088.23
   551.4 2092.93   561.4 2094.86   611.5 2103.02   661.7 2109.63   691.7  2114.7
#Mann= 3 , 0 , 0
       0      .1       0   242.1    .045       0   257.1      .1       0
Bank Sta=242.1,257.1
XS Rating Curve= 0 ,0
Exp/Cntr=0.3,0.1

Type RM Length L Ch R = 1 ,25622.7 ,105.8,102.7,99.7
XS GIS Cut Line= 3
     2151658.365      260888.478     2151952.764      260773.027
     2152441.987      260770.141
#Sta/Elev= 30
       0 2121.74    19.8 2116.71    39.5 2110.74    88.9 2094.29   118.6    2085
   148.2 2073.62   158.1 2070.29   177.9  2065.4   187.8 2064.12   197.6 2063.57
   227.3 2063.09   256.9 2061.72   296.5 2058.75   346.2 2055.98   376.1 2053.62
   406.1 2053.07   411.8 2053.09   426.8  2053.8     446  2056.6     456 2056.79
   535.9 2054.39   555.8 2054.55   575.8 2055.79   595.8 2059.02   625.7 2066.05
   655.7 2074.44   705.6 2089.81   725.6 2095.13   745.6 2098.77   805.5 2105.85
#Mann= 3 , 0 , 0
       0      .1       0   411.8    .045       0   426.8      .1       0
Bank Sta=411.8,426.8
XS Rating Curve= 0 ,0
Exp/Cntr=0.3,0.1

Type RM Length L Ch R = 1 ,25520   ,153.4,153.5,153.7
XS GIS Cut Line= 2
     2151664.484      260931.369     2152541.437      260803.633
#Sta/Elev= 30
       0 2115.93    60.4 2101.59   100.7  2091.1   130.9 2082.22   181.3 2065.71
   201.4 2060.71   211.5 2059.11   221.6 2058.24     292 2053.96   352.5 2051.51
   392.8 2048.24   402.8 2047.91   414.2 2048.22   429.2 2048.94   543.8 2052.24
   553.9 2053.04     564 2054.75   584.1  2059.5   604.2 2065.62   614.3 2069.76
   624.4  2074.7   654.6 2090.43   664.7 2094.58   674.7 2097.96   694.9 2103.29
     715 2107.36   735.2 2110.13   795.6 2114.15   825.8 2117.08   886.2 2127.52
#Mann= 3 , 0 , 0
       0      .1       0   414.2    .045       0   429.2      .1       0
Bank Sta=414.2,429.2
XS Rating Curve= 0 ,0
Exp/Cntr=0.3,0.1

Type RM Length L Ch R = 1 ,25366.4 ,212.1,212.7,213.3
XS GIS Cut Line= 2
     2151679.223      261073.843     2152588.109      260960.846
#Sta/Elev= 30
       0 2099.45    40.3 2090.33    90.6 2077.73   120.8 2069.53     151 2059.68
     161 2057.46   181.2 2055.52   291.9 2049.95     436 2045.38     451 2045.22
   493.2 2045.02   503.2  2045.2   513.3 2046.51   523.4  2049.7   533.4 2054.23
   553.6 2064.22   583.8 2080.66   664.3 2128.98   684.4 2140.16   694.5 2144.68
   714.6 2151.29   734.7 2158.95   744.8 2162.02   754.8 2163.84   805.2 2168.92
   815.2 2169.73   875.6 2171.72   885.7 2172.38   895.8 2174.03   915.9 2178.58
#Mann= 3 , 0 , 0
       0     .11       0     436    .045       0     451     .11       0
Bank Sta=436,451
XS Rating Curve= 0 ,0
Exp/Cntr=0.3,0.1

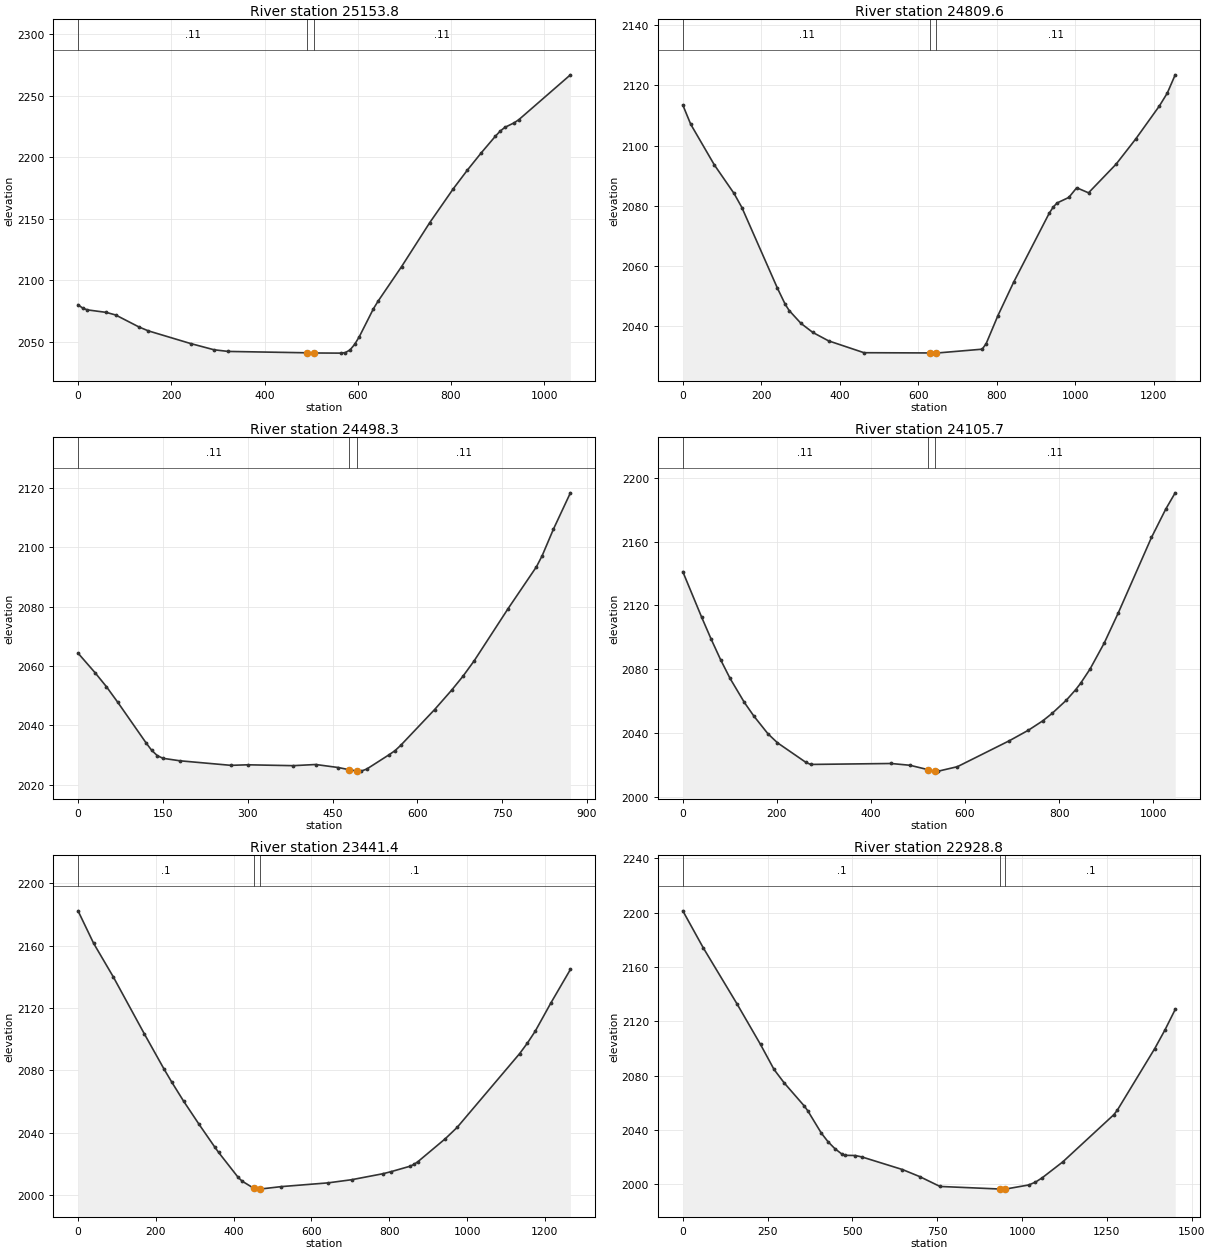
Type RM Length L Ch R = 1 ,25153.8 ,342.9,344.2,345.5
XS GIS Cut Line= 2
     2151637.463      261277.728     2152688.824      261177.014
#Sta/Elev= 30
       0  2080.3    10.1 2077.58    20.1 2076.16    60.4 2074.13    80.5 2072.05
   130.8 2062.28   150.9 2059.12   241.4 2048.86   291.7 2043.79   321.9 2042.45
   491.1 2041.34   506.1 2041.19   563.3 2041.07   573.4 2041.52   583.4 2043.66
   593.5 2048.24   603.5 2054.52   633.7 2077.12   643.8 2083.33   694.1 2111.31
   754.4 2146.92   804.7  2174.3   834.9 2189.43   865.1 2203.65   895.2 2217.04
   905.3  2221.1   915.4  2224.2   935.5 2227.94   945.5 2230.47  1056.2 2266.87
#Mann= 3 , 0 , 0
       0     .11       0   491.1    .045       0   506.1     .11       0
Bank Sta=491.1,506.1
XS Rating Curve= 0 ,0
Exp/Cntr=0.3,0.1

Type RM Length L Ch R = 1 ,24809.6 ,314.1,311.2,308.6
XS GIS Cut Line= 2
     2151511.187      261594.432     2152764.824      261548.921
#Sta/Elev= 30
       0 2113.48    20.1  2107.1    80.3 2093.59   130.5  2084.1   150.5 2079.42
   240.9 2052.66   260.9 2047.26     271 2045.19   301.1 2040.91   331.2 2037.91
   371.3 2035.11   461.6 2031.17   630.7 2031.09   642.3 2031.03   645.7 2031.05
   762.7 2032.34   772.8 2034.16   802.9 2043.51     843 2054.62   933.3 2077.46
   943.4  2079.5   953.4 2080.92   983.5 2082.77  1003.6 2085.98  1033.7  2084.3
  1103.9 2093.82  1154.1 2102.22  1214.3 2113.18  1234.4 2117.45  1254.5 2123.51
#Mann= 3 , 0 , 0
       0     .11       0   630.7    .045       0   645.7     .11       0
Bank Sta=630.7,645.7
XS Rating Curve= 0 ,0
Exp/Cntr=0.3,0.1

Type RM Length L Ch R = 1 ,24498.3 ,396,392.6,388.9
XS GIS Cut Line= 2
     2151718.058       261950.25     2152578.641      261817.853
#Sta/Elev= 30
       0 2064.36      30  2057.8      50 2053.12    70.1 2047.86   120.1  2034.2
   130.1 2031.67   140.1 2029.86   150.1 2028.95   180.2 2028.11   270.2 2026.58
   300.2 2026.76   380.3 2026.47   420.3 2026.86   460.4 2025.84   479.1 2025.12
   494.1 2024.66   500.4 2024.63   510.4 2025.31   550.4 2030.19   560.5 2031.52
   570.5 2033.29   630.5 2045.35   660.5 2051.86   680.6 2056.56   700.6  2061.8
   760.6 2079.38   810.7 2093.46   820.7 2097.15   840.7 2106.12   870.7 2118.34
#Mann= 3 , 0 , 0
       0     .11       0   479.1    .045       0   494.1     .11       0
Bank Sta=479.1,494.1
XS Rating Curve= 0 ,0
Exp/Cntr=0.3,0.1

Type RM Length L Ch R = 1 ,24105.7 ,667,664.3,661.3
XS GIS Cut Line= 2
     2151775.982      262409.504     2152773.099      262090.923
#Sta/Elev= 30
       0 2141.17    40.3 2112.43    60.4 2098.72    80.5 2085.83   100.6 2074.12
   130.8 2059.12     151 2050.56   181.2 2039.35   201.3 2033.75   261.7 2021.47
   271.8 2020.17   442.9 2020.76   483.1 2019.64   520.5 2016.95   535.5 2016.06
   543.5 2015.97   583.8 2018.76   694.5 2035.09   734.8 2041.67     765 2047.49
   785.1  2052.2   815.3 2060.47   835.4 2067.15   845.5 2071.02   865.6 2079.97
   895.8  2096.3     926 2115.42   996.4 2162.66  1026.6 2180.38  1046.8 2190.67
#Mann= 3 , 0 , 0
       0     .11       0   520.5    .045       0   535.5     .11       0
Bank Sta=520.5,535.5
XS Rating Curve= 0 ,0
Exp/Cntr=0.3,0.1

Type RM Length L Ch R = 1 ,23441.4 ,511.4,512.6,514.1
XS GIS Cut Line= 3
     2151925.058      263047.812     2152602.174      262741.602
     2153122.382      262694.316
#Sta/Elev= 30
       0 2182.37    40.2 2161.47    90.4 2140.11   170.7 2103.34   220.9 2080.96
     241 2072.48   271.1 2060.41   311.3 2045.37   351.5 2030.85   361.5 2027.39
   411.7 2011.39   421.8 2009.01   451.6 2004.46     462  2003.9   466.6  2003.9
   522.2 2005.51   642.7 2007.92     703 2009.93   783.3 2013.76   803.4 2015.02
   853.6  2018.6   863.7 2019.82   873.7 2021.54     944 2036.24   974.2 2043.44
  1134.9 2090.78    1155 2097.58  1175.1  2105.2  1215.3  2123.3  1265.5 2144.79
#Mann= 3 , 0 , 0
       0      .1       0   451.6    .045       0   466.6      .1       0
Bank Sta=451.6,466.6
XS Rating Curve= 0 ,0
Exp/Cntr=0.3,0.1

Type RM Length L Ch R = 1 ,22928.8 ,397.4,399.1,400.3
XS GIS Cut Line= 3
       2151799.9      263120.164     2152421.419      263261.812
     2153181.997      262971.639
#Sta/Elev= 30
       0 2201.34    59.8 2174.33   159.4 2133.02   229.1 2102.99   268.9 2084.63
   298.8 2074.74   358.6 2057.58   368.5 2054.15   408.4 2037.76   428.3 2031.37
   448.2 2026.37   468.1  2022.5   478.1 2021.43     508 2021.29   527.9 2020.24
   647.5 2010.96   697.8 2005.83   758.1 1998.52     936 1996.61     949 1996.55
     951 1996.59  1019.4 1999.59  1039.5 2001.68  1059.6 2004.91  1119.9 2016.55
  1270.6 2051.32  1280.7 2054.56  1391.2 2099.97  1421.4 2113.72  1451.5 2128.76
#Mann= 3 , 0 , 0
       0      .1       0     936    .045       0     951      .1       0
Bank Sta=936,951
XS Rating Curve= 0 ,0
Exp/Cntr=0.3,0.1

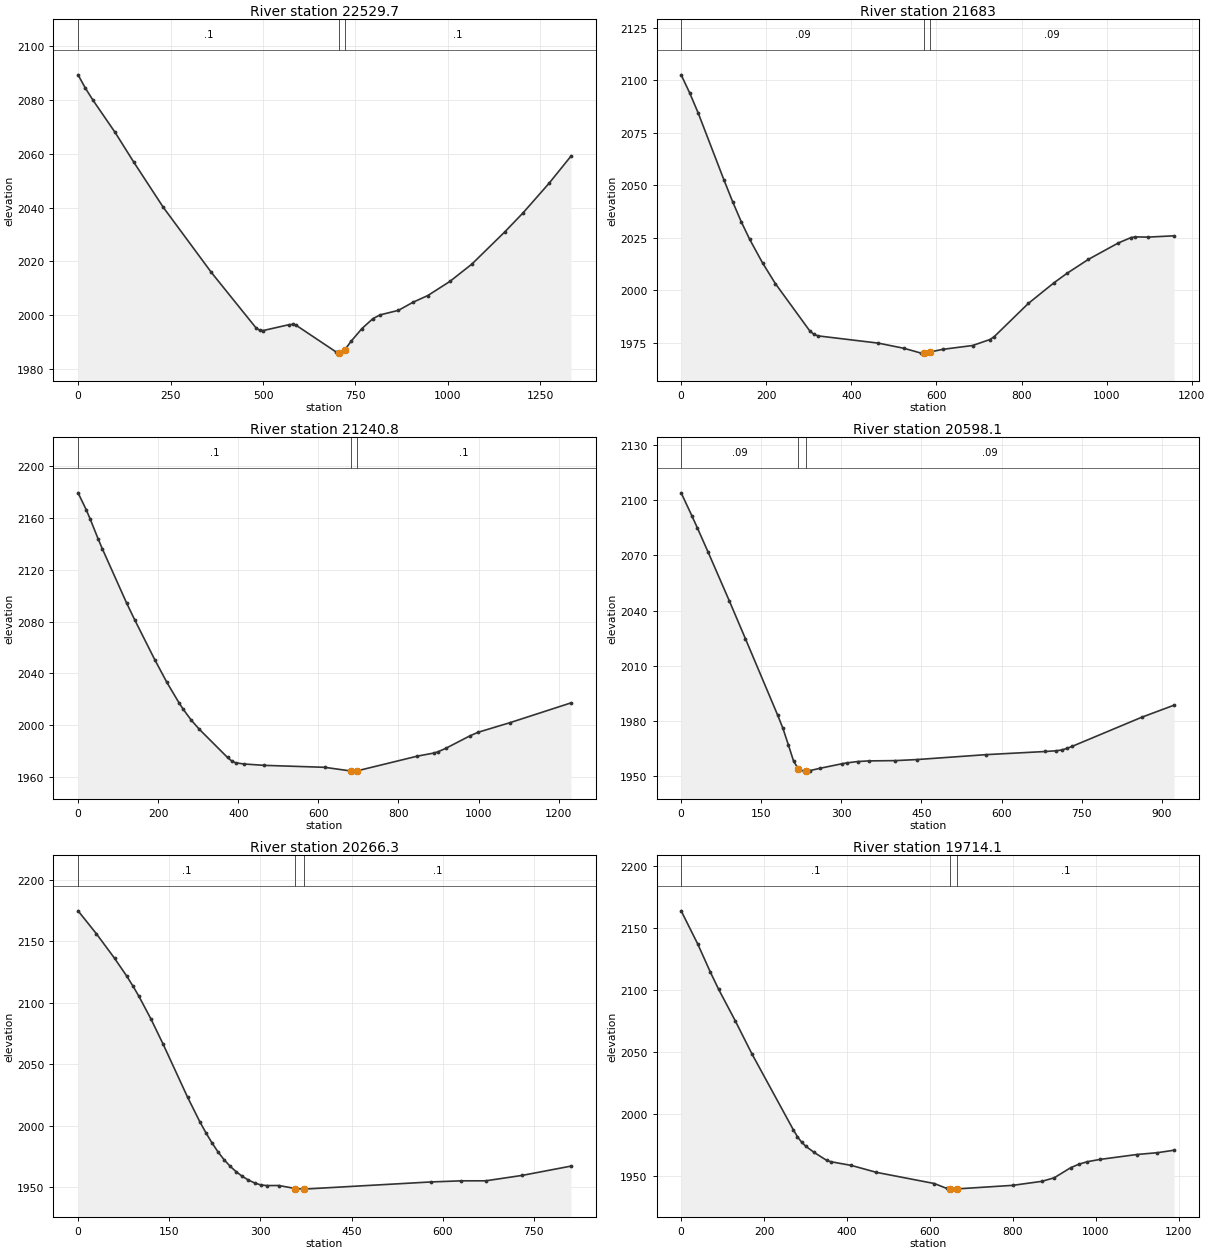
Type RM Length L Ch R = 1 ,22529.7 ,837.8,846.7,855
XS GIS Cut Line= 4
     2152329.489      264037.204     2152621.882      263582.503
     2152952.571      263483.677     2153398.045      263516.626
#Sta/Elev= 30
       0 2089.27      20 2084.28      40 2079.93   100.1  2067.9   150.2 2056.95
   230.2 2040.13   360.4 2015.91   480.5 1995.43   490.5 1994.49   500.6 1994.35
   570.2 1996.52     580 1996.64   589.9 1996.27   698.4 1986.32   705.3 1986.07
   708.2 1985.96   720.3 1987.04   737.8 1990.31   767.4 1995.08     797 1998.76
   816.7 2000.16     866 2001.84   905.6 2004.86   945.3 2007.32  1004.9 2012.55
  1064.4 2018.99  1153.8 2030.99  1203.4 2038.09  1272.9 2048.95  1332.4 2059.06
#Mann= 3 , 0 , 0
       0      .1       0   705.3    .045       0   720.3      .1       0
Bank Sta=705.3,720.3
XS Rating Curve= 0 ,0
Exp/Cntr=0.3,0.1

Type RM Length L Ch R = 1 ,21683   ,440.6,442.2,444.3
XS GIS Cut Line= 2
     2152321.712      264187.091     2153472.323      264320.991
#Sta/Elev= 30
       0 2102.64    20.2 2093.96    40.3 2084.34   100.7 2052.55   120.9  2042.3
     141  2032.8   161.2 2024.27   191.4 2013.07   221.6  2003.2   302.2 1980.76
   312.3 1979.05   322.3 1978.34   463.4  1974.9   523.8 1972.43   564.1 1970.14
   569.9  1970.2   584.9 1970.67   614.4 1971.93     685 1973.77   725.2 1976.58
   735.3 1977.88   815.9 1993.78   876.3 2003.64   906.6  2008.1   956.9 2014.75
  1027.4 2022.58  1057.6 2025.18  1067.7 2025.48  1097.9 2025.38  1158.4    2026
#Mann= 3 , 0 , 0
       0     .09       0   569.9    .045       0   584.9     .09       0
Bank Sta=569.9,584.9
XS Rating Curve= 0 ,0
Exp/Cntr=0.3,0.1

Type RM Length L Ch R = 1 ,21240.8 ,649.6,642.6,635.5
XS GIS Cut Line= 2
     2152160.761      264503.037     2153360.613      264776.107
#Sta/Elev= 30
       0 2179.11    20.2 2166.21    30.3 2158.92    50.4 2143.42    60.5 2136.08
     121 2094.37   141.2 2081.43   191.6 2050.54   221.9 2033.04   252.2 2017.31
   262.2 2012.58   282.4  2004.1   302.6 1997.05   373.2 1975.27   383.3 1972.66
   393.4 1971.17   413.5 1970.29     464 1969.22   615.3 1967.71   680.9 1964.88
   685.9 1964.76   695.9 1964.92   847.2 1976.32   887.6 1978.64   897.7 1979.55
   917.9 1982.29   978.4 1991.94   998.6 1994.68  1079.2 2002.17  1230.5 2017.31
#Mann= 3 , 0 , 0
       0      .1       0   680.9    .045       0   695.9      .1       0
Bank Sta=680.9,695.9
XS Rating Curve= 0 ,0
Exp/Cntr=0.3,0.1

Type RM Length L Ch R = 1 ,20598.1 ,335.4,331.8,328
XS GIS Cut Line= 2
     2152218.685      265074.001      2153141.33      265057.451
#Sta/Elev= 30
       0 2104.07    20.1 2091.58    30.1 2085.17    50.2 2072.02    90.3 2045.23
   120.4 2024.68   180.6 1983.24   190.6 1975.94   200.6 1967.11   210.6 1958.07
   219.2 1954.05   220.7 1953.35   230.7  1952.7   234.2 1952.79   240.7 1952.96
   260.8  1954.3   300.9  1956.7   310.9 1957.21     331 1957.93   351.1 1958.26
   401.2 1958.42   441.3 1958.99   571.7 1961.68   682.1 1963.38   702.1 1963.78
   712.2 1964.18   722.2 1965.06   732.2 1966.19   862.6 1982.04   922.8 1988.56
#Mann= 3 , 0 , 0
       0     .09       0   219.2    .045       0   234.2     .09       0
Bank Sta=219.2,234.2
XS Rating Curve= 0 ,0
Exp/Cntr=0.3,0.1

Type RM Length L Ch R = 1 ,20266.3 ,553.7,552.2,550.8
XS GIS Cut Line= 2
     2152171.192      265449.215     2152968.926      265303.923
#Sta/Elev= 30
       0 2174.58      30 2156.07    60.1 2135.99    80.1 2121.54    90.1 2113.62
   100.1 2105.16   120.1 2086.53   140.2    2066   180.2 2023.16   200.2 2003.34
   210.2 1994.37   220.2 1986.16   230.2 1978.76   240.2  1972.4   250.3 1967.01
   260.3 1962.53   270.3 1958.82   280.3 1955.85   290.3 1953.54   300.3 1951.92
   310.3 1951.36   330.4 1951.39   357.4 1948.95   370.4 1948.46   372.4 1948.51
   580.6  1954.3   630.7  1955.2   670.7 1955.22   730.8 1959.63   810.9 1967.16
#Mann= 3 , 0 , 0
       0      .1       0   357.4    .045       0   372.4      .1       0
Bank Sta=357.4,372.4
XS Rating Curve= 0 ,0
Exp/Cntr=0.3,0.1

Type RM Length L Ch R = 1 ,19714.1 ,807.3,815.2,820.2
XS GIS Cut Line= 3
     2152093.539      265638.859     2152509.848      265952.047
     2153155.338      265780.918
#Sta/Elev= 30
       0 2163.54    40.1 2136.76    70.1 2114.45    90.2 2100.46   130.2 2075.18
   170.3  2048.6   270.5 1987.24   280.5 1981.65   290.5 1977.23   300.6 1973.94
   320.6 1969.01   350.6 1962.64   360.7  1961.5   410.8 1958.47   470.9 1952.92
   610.7 1943.91   640.6 1939.97   649.3 1939.47   650.5  1939.4   664.3 1939.56
     800 1942.45   869.8 1945.68   899.7  1948.5   939.6 1956.66   959.5 1959.49
   979.4 1961.45  1009.3 1963.29    1099 1967.28  1148.9 1968.75  1188.8 1970.74
#Mann= 3 , 0 , 0
       0      .1       0   649.3    .045       0   664.3      .1       0
Bank Sta=649.3,664.3
XS Rating Curve= 0 ,0
Exp/Cntr=0.3,0.1

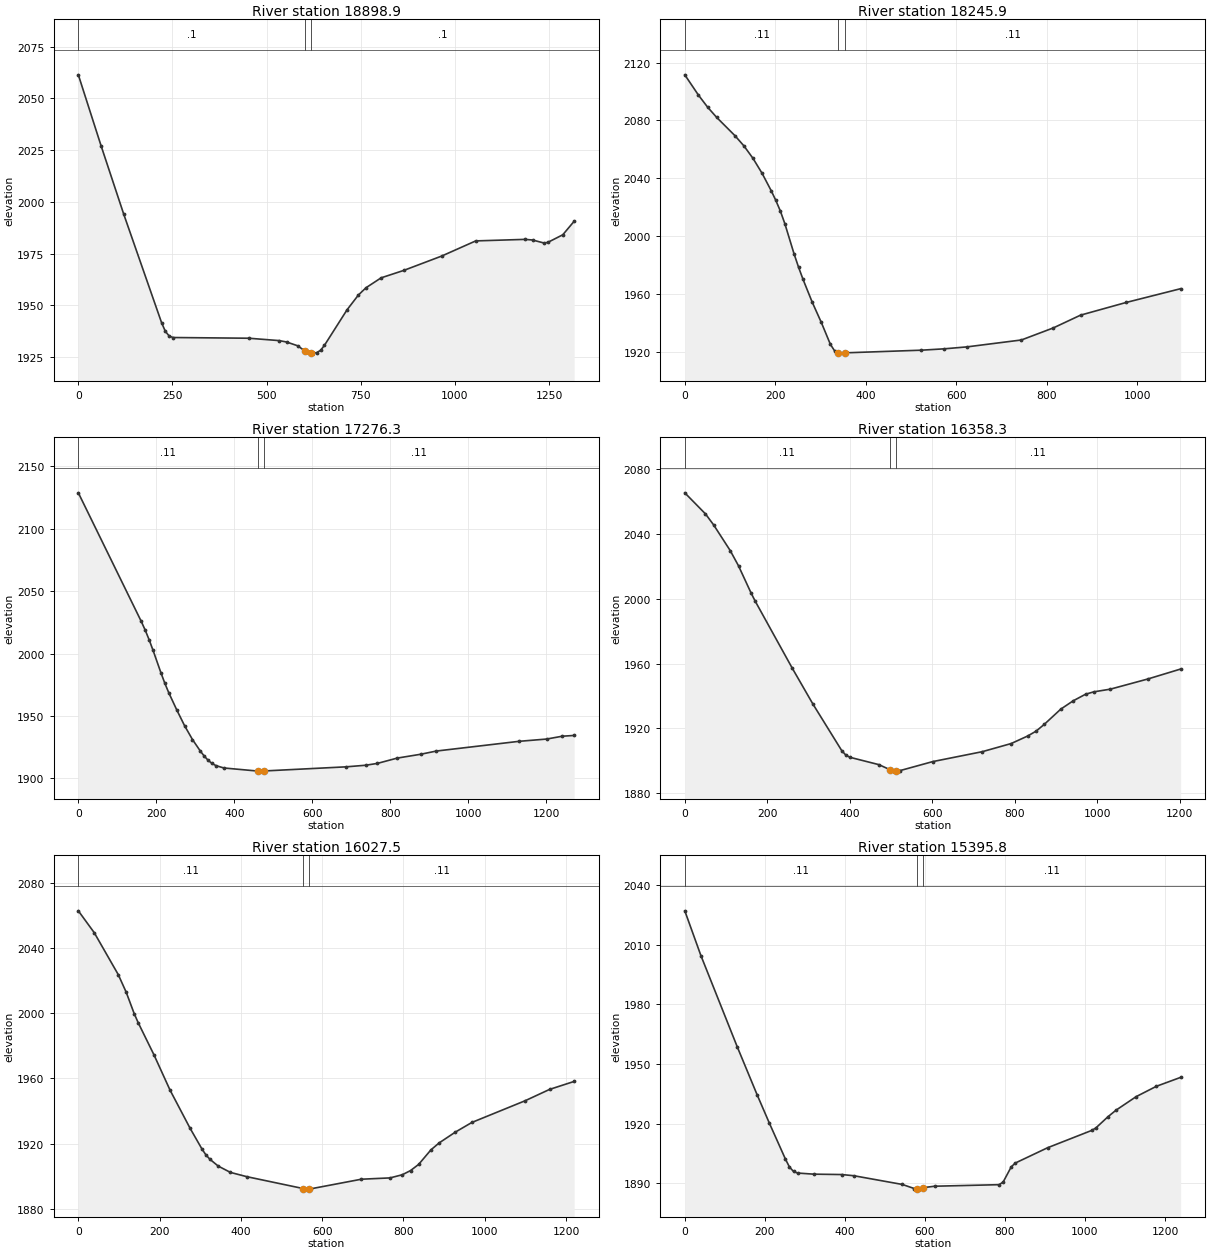
Type RM Length L Ch R = 1 ,18898.9 ,652.7,653,653.4
XS GIS Cut Line= 2
      2152289.07      266660.893     2153602.547      266566.309
#Sta/Elev= 30
       0 2061.35    60.3 2027.14   120.6 1994.02   221.2 1941.57   231.2 1937.41
   241.3 1935.19   251.3 1934.45   452.4 1934.11   532.8 1932.97   552.9  1932.3
     583 1930.43   602.8 1927.78   617.8 1926.93   623.3 1926.91   633.3 1927.17
   643.4 1928.27   653.4  1930.6   713.7 1947.84   743.9 1954.99     764 1958.49
   804.2 1963.28   864.5 1966.88     965  1973.8  1055.5 1981.12  1186.2 1981.86
  1206.3 1981.56  1236.5 1980.12  1246.5 1980.37  1286.7 1984.08  1316.9 1990.62
#Mann= 3 , 0 , 0
       0      .1       0   602.8    .045       0   617.8      .1       0
Bank Sta=602.8,617.8
XS Rating Curve= 0 ,0
Exp/Cntr=0.3,0.1

Type RM Length L Ch R = 1 ,18245.9 ,971.1,969.6,967
XS GIS Cut Line= 2
     2152234.177      267147.866     2153328.043      267085.802
#Sta/Elev= 30
       0 2111.51    30.2 2097.49    50.3 2089.23    70.4 2082.14   110.6 2069.58
   130.7 2062.44   150.8  2053.8   170.9 2043.46     191 2031.47     201 2024.91
   211.1 2017.54   221.1 2008.74   241.2 1988.16   251.3 1978.77   261.3 1970.28
   281.4 1954.68   301.6 1940.62   321.6 1925.54   331.7 1920.63   339.4 1919.69
   341.8  1919.4   354.4  1919.6   522.7 1921.43   572.9 1922.36   623.2  1923.7
   743.8 1928.48   814.2 1936.79   874.5 1945.62     975 1954.35  1095.6 1963.88
#Mann= 3 , 0 , 0
       0     .11       0   339.4    .045       0   354.4     .11       0
Bank Sta=339.4,354.4
XS Rating Curve= 0 ,0
Exp/Cntr=0.3,0.1

Type RM Length L Ch R = 1 ,17276.3 ,920.9,918,916.1
XS GIS Cut Line= 2
     2152329.203      268101.924     2153564.537      267801.643
#Sta/Elev= 30
       0 2128.86   161.4 2025.79   171.5 2018.82   181.6 2011.08   191.7 2002.55
   211.9 1984.56     222  1976.1   232.1 1968.52   252.2 1955.03   272.4 1942.27
   292.6  1931.2   312.8 1921.94   322.9 1917.89     333 1914.48     343 1911.98
   353.1 1910.24   373.3 1908.38   460.7 1905.89   464.1 1905.86   475.7 1905.98
   686.1 1909.29   736.6 1910.57   766.8 1912.05   817.3 1916.28   877.8 1919.38
   918.2 1921.96    1130 1929.74  1200.7 1931.56    1241 1933.84  1271.3 1934.45
#Mann= 3 , 0 , 0
       0     .11       0   460.7    .045       0   475.7     .11       0
Bank Sta=460.7,475.7
XS Rating Curve= 0 ,0
Exp/Cntr=0.3,0.1

Type RM Length L Ch R = 1 ,16358.3 ,330,330.8,331.6
XS GIS Cut Line= 2
     2152607.603      268959.037     2153765.991      268637.869
#Sta/Elev= 30
       0 2065.54    50.1 2052.53    70.1 2045.66   110.2 2029.83   130.2 2020.46
   160.3 2003.87   170.3  1998.8   260.4 1957.28   310.5 1935.11   380.7 1906.21
   390.7 1903.47   400.7 1902.15   470.8 1897.62     497 1894.56   510.9 1893.63
     512 1893.66   520.9 1893.89     601 1899.51   721.2 1905.64   791.4 1910.68
   831.4 1915.34   851.5  1918.3   871.5 1922.51   911.6 1931.94   941.6 1937.06
   971.7 1941.14   991.7 1942.61  1031.8 1944.27    1122  1950.5  1202.1 1956.69
#Mann= 3 , 0 , 0
       0     .11       0     497    .045       0     512     .11       0
Bank Sta=497,512
XS Rating Curve= 0 ,0
Exp/Cntr=0.3,0.1

Type RM Length L Ch R = 1 ,16027.5 ,636.3,631.7,627.1
XS GIS Cut Line= 3
     2152656.091      269097.793     2152955.761      269191.479
     2153836.427      268978.134
#Sta/Elev= 30
       0 2062.88    39.2 2049.44    98.1 2023.78   117.7 2012.97   137.4  1999.8
   147.2 1994.24   186.4 1974.31   225.7 1952.78   274.7  1929.5   304.2 1916.64
     314 1913.01     324  1910.3   344.2 1906.15   374.4 1902.26   414.7 1899.64
   553.8 1892.33   565.7    1892   568.8 1892.04   696.6 1898.09     767 1898.89
   797.2 1900.83   817.4 1903.38   837.5  1907.2   867.7 1916.12   887.9 1920.38
   928.1 1927.07   968.4 1932.94  1099.3 1946.25  1159.7 1953.24  1220.1 1958.13
#Mann= 3 , 0 , 0
       0     .11       0   553.8    .045       0   568.8     .11       0
Bank Sta=553.8,568.8
XS Rating Curve= 0 ,0
Exp/Cntr=0.3,0.1

Type RM Length L Ch R = 1 ,15395.8 ,1008.3,1014.7,1020.5
XS GIS Cut Line= 3
     2153078.005      270029.045     2153382.087      269721.162
     2154115.686      269386.671
#Sta/Elev= 30
       0 2027.05    40.2 2004.57   130.8 1958.79   181.1 1934.36   211.3 1920.28
   251.6 1902.14   261.6 1898.19   271.7 1895.98   281.8 1895.18     322 1894.62
   392.5 1894.42   422.7 1893.82   543.6 1889.44   573.8 1887.36   581.3 1887.16
   583.9 1887.09   596.3 1887.84   624.2 1888.55   785.5 1889.33   795.6 1890.68
   815.7 1898.28   825.8  1900.2   906.4 1907.89  1017.3 1916.65  1027.4  1917.9
  1057.6 1923.52  1077.7 1926.81  1128.1 1933.63  1178.5 1938.81    1239 1943.29
#Mann= 3 , 0 , 0
       0     .11       0   581.3    .045       0   596.3     .11       0
Bank Sta=581.3,596.3
XS Rating Curve= 0 ,0
Exp/Cntr=0.3,0.1

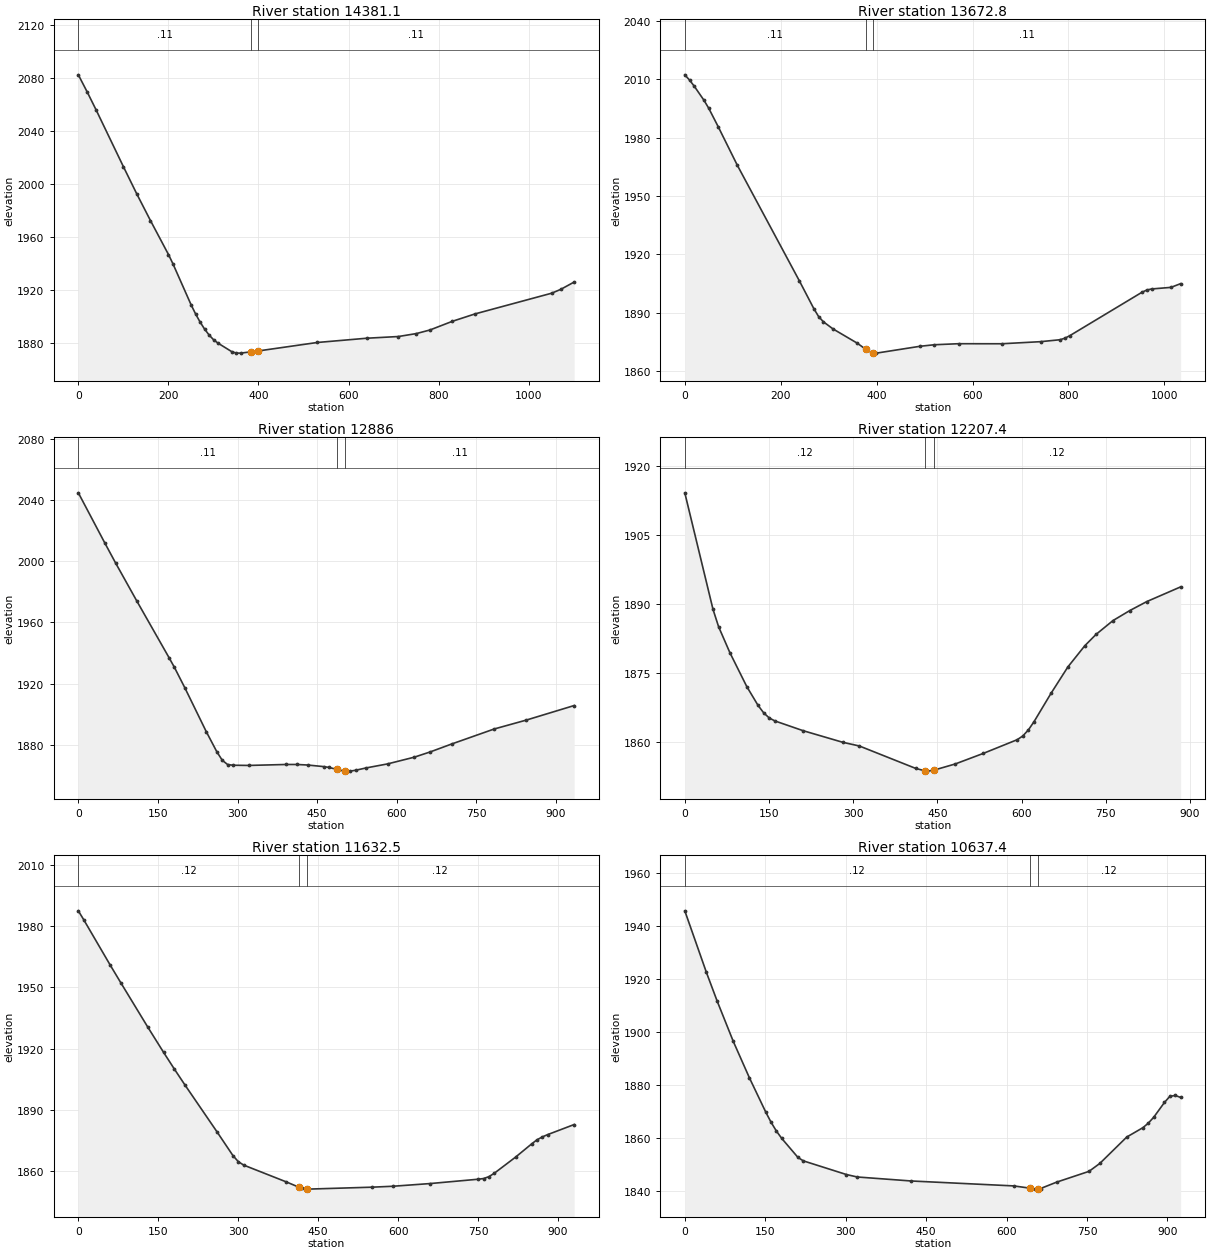
Type RM Length L Ch R = 1 ,14381.1 ,709.1,708.3,706.8
XS GIS Cut Line= 2
     2153157.827      270363.535     2154248.722      270215.295
#Sta/Elev= 30
       0 2082.12      20 2068.98      40  2055.3   100.1 2012.86   130.1 1992.11
   160.1 1972.27   200.2  1946.6   210.2 1939.53   250.2 1908.85   260.2 1901.93
   270.2  1895.8   280.2 1890.48   290.2    1886   300.2 1882.39   310.3 1879.77
   340.3 1873.46   350.3 1872.32   360.3 1872.28   384.2 1873.29   399.2 1873.91
   530.4  1880.3   640.5 1883.52   710.6  1884.8   750.6 1887.03   780.6 1889.72
   830.7  1896.3   880.7 1901.84  1050.9 1917.46  1070.9 1920.32  1100.9 1925.88
#Mann= 3 , 0 , 0
       0     .11       0   384.2    .045       0   399.2     .11       0
Bank Sta=384.2,399.2
XS Rating Curve= 0 ,0
Exp/Cntr=0.3,0.1

Type RM Length L Ch R = 1 ,13672.8 ,785.6,786.7,782.1
XS GIS Cut Line= 3
      2153317.47      270804.454     2153541.731      271002.108
      2154262.57      270858.112
#Sta/Elev= 30
       0 2012.35      10 2009.62    19.9 2006.44    39.9  1999.3    49.8 1995.22
    69.8 1985.61   109.6 1965.82   239.1 1906.35     269 1892.18     279 1888.09
     289 1885.38     309 1881.73   359.4 1874.42   377.1 1871.29   389.6 1869.57
   392.1  1869.5   399.6 1869.27   490.2 1872.78   520.5 1873.58   570.8 1874.11
   661.4 1874.09     742 1875.16   782.3 1876.15   792.3 1876.91   802.4 1878.17
   953.5 1900.58   963.5 1901.71   973.6 1902.26  1013.9 1903.08    1034 1904.99
#Mann= 3 , 0 , 0
       0     .11       0   377.1    .045       0   392.1     .11       0
Bank Sta=377.1,392.1
XS Rating Curve= 0 ,0
Exp/Cntr=0.3,0.1

Type RM Length L Ch R = 1 ,12886   ,672.5,678.7,687.9
XS GIS Cut Line= 2
     2153480.366      271672.283      2154374.28      271400.113
#Sta/Elev= 30
       0 2044.68    50.2 2011.71    70.3 1998.78   110.5 1973.79   170.8 1937.03
   180.9 1930.72     201 1917.06   241.1 1888.58   261.2 1875.31   271.3 1869.86
   281.3 1867.09   291.4 1866.63   321.5  1866.5   391.9 1867.13     412 1867.12
     432 1866.78   462.2 1865.74   472.2 1865.21   487.4  1863.9   502.4 1862.78
   512.4  1862.8   522.5 1863.34   542.6 1864.89   582.8  1867.5     633 1871.89
   663.1 1875.33   703.3 1880.48   783.7 1890.32     844 1896.12   934.4 1905.65
#Mann= 3 , 0 , 0
       0     .11       0   487.4    .045       0   502.4     .11       0
Bank Sta=487.4,502.4
XS Rating Curve= 0 ,0
Exp/Cntr=0.3,0.1

Type RM Length L Ch R = 1 ,12207.4 ,590.6,574.9,559.5
XS GIS Cut Line= 2
     2153786.767      272086.925     2154668.037      272029.001
#Sta/Elev= 30
       0 1914.08    50.2 1888.85    60.2 1885.07    80.3 1879.45   110.4  1872.1
   130.5 1868.02   140.5 1866.41   150.5 1865.29   160.6 1864.65   210.8 1862.54
     281 1860.04   311.1 1859.22   411.5 1854.36   428.7 1853.82   431.6 1853.78
   443.7 1853.99   481.7 1855.33   531.9 1857.63   592.1 1860.59   602.2 1861.41
   612.2 1862.74   622.2 1864.52   652.3 1870.63   682.4 1876.36   712.6 1880.96
   732.6 1883.41   762.7  1886.4   792.8 1888.58     823 1890.52   883.2  1893.7
#Mann= 3 , 0 , 0
       0     .12       0   428.7    .045       0   443.7     .12       0
Bank Sta=428.7,443.7
XS Rating Curve= 0 ,0
Exp/Cntr=0.3,0.1

Type RM Length L Ch R = 1 ,11632.5 ,986.1,995.1,1002.6
XS GIS Cut Line= 2
     2154085.277      272868.412     2154758.059      272226.038
#Sta/Elev= 30
       0 1987.65      10 1983.33      60  1960.9      80 1952.17     130 1930.64
     160 1918.08     180 1909.96     200 1902.09   260.1 1879.08   290.1 1867.36
   300.1 1864.42   310.1 1862.72   390.1 1854.46   413.2 1851.91   420.1 1851.21
   428.2 1850.96   430.1  1850.9   550.1 1851.85   590.1 1852.31   660.1 1853.64
   750.2 1855.77   760.2  1856.1   770.2 1857.01   780.2 1858.67   820.2 1866.61
   850.2 1873.07   860.2 1875.09   870.2 1876.52   880.2 1877.66   930.2 1882.64
#Mann= 3 , 0 , 0
       0     .12       0   413.2    .045       0   428.2     .12       0
Bank Sta=413.2,428.2
XS Rating Curve= 0 ,0
Exp/Cntr=0.3,0.1

Type RM Length L Ch R = 1 ,10637.4 ,635.7,636.3,636.9
XS GIS Cut Line= 2
     2154381.757      273419.561      2155240.79      273077.468
#Sta/Elev= 30
       0 1945.79    40.2 1922.57    60.3  1911.7    90.4 1896.44   120.6 1882.62
   150.8 1869.79   160.8  1865.9   170.9 1862.52   180.9 1859.74   211.1 1852.56
   221.1 1851.28   301.5 1846.11   321.6 1845.19   422.1 1843.68   613.1 1841.82
   642.8 1840.99   653.3  1840.6   657.8  1840.7   663.3 1840.82   693.5 1843.25
   753.8 1847.32   773.9 1850.31   824.1 1860.28   854.3 1863.83   864.3 1865.53
   874.4 1867.76   894.5 1873.38   904.5 1875.67   914.6 1876.01   924.6 1875.25
#Mann= 3 , 0 , 0
       0     .12       0   642.8    .045       0   657.8     .12       0
Bank Sta=642.8,657.8
XS Rating Curve= 0 ,0
Exp/Cntr=0.3,0.1