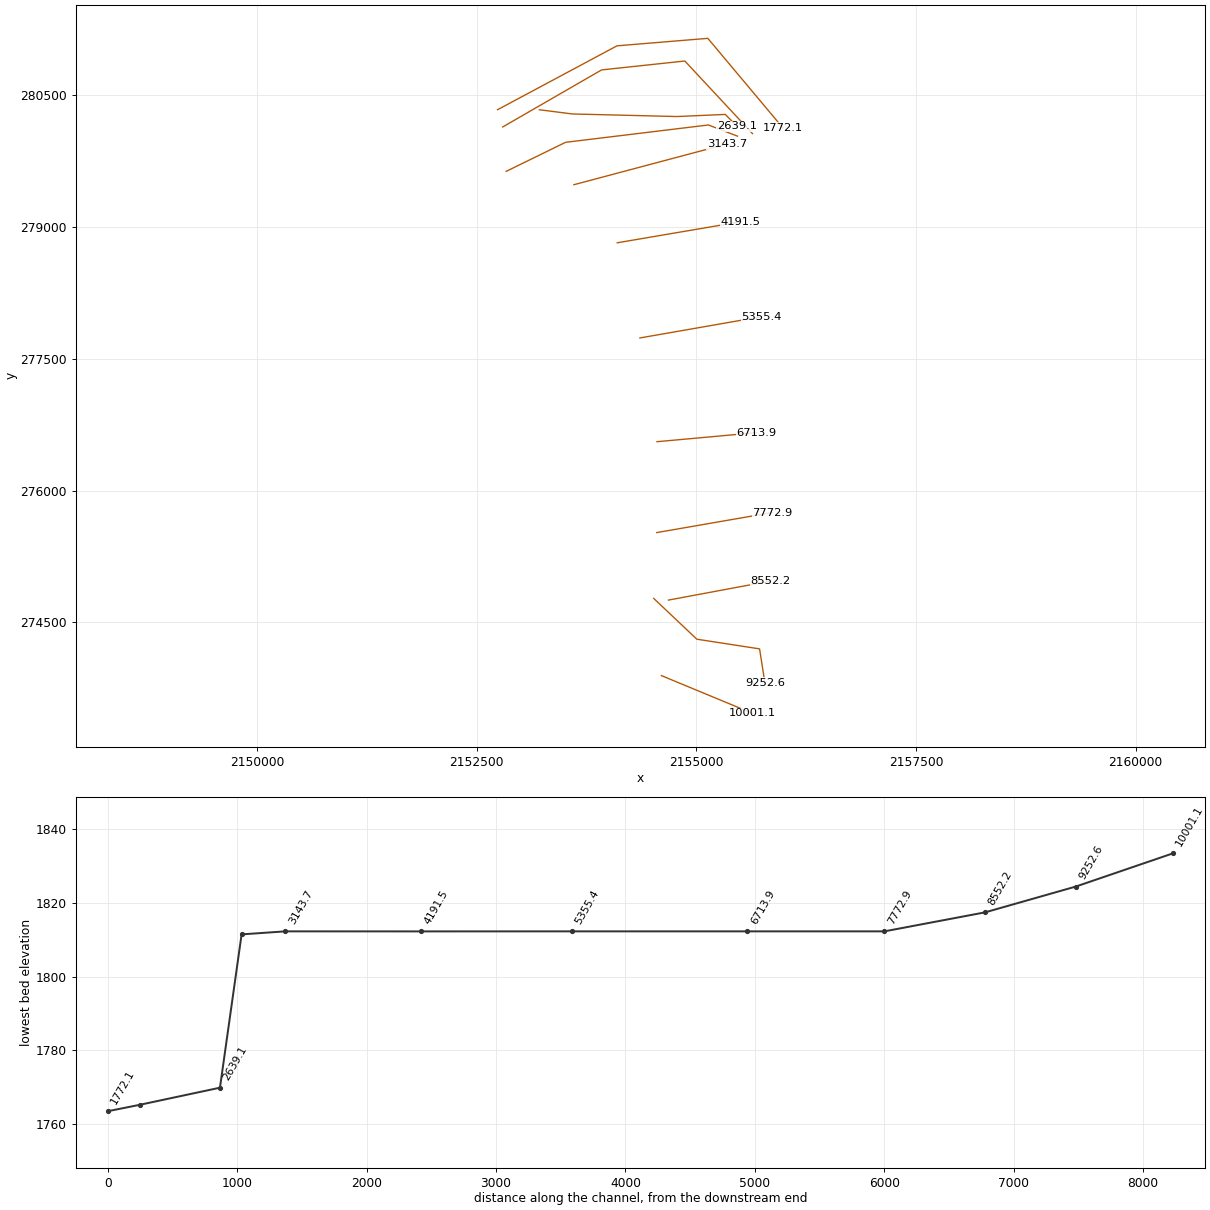
HEC-RAS study HartsRun.prj: HartsRun

--- HartsRun.g01 (geometry) --- (continued)

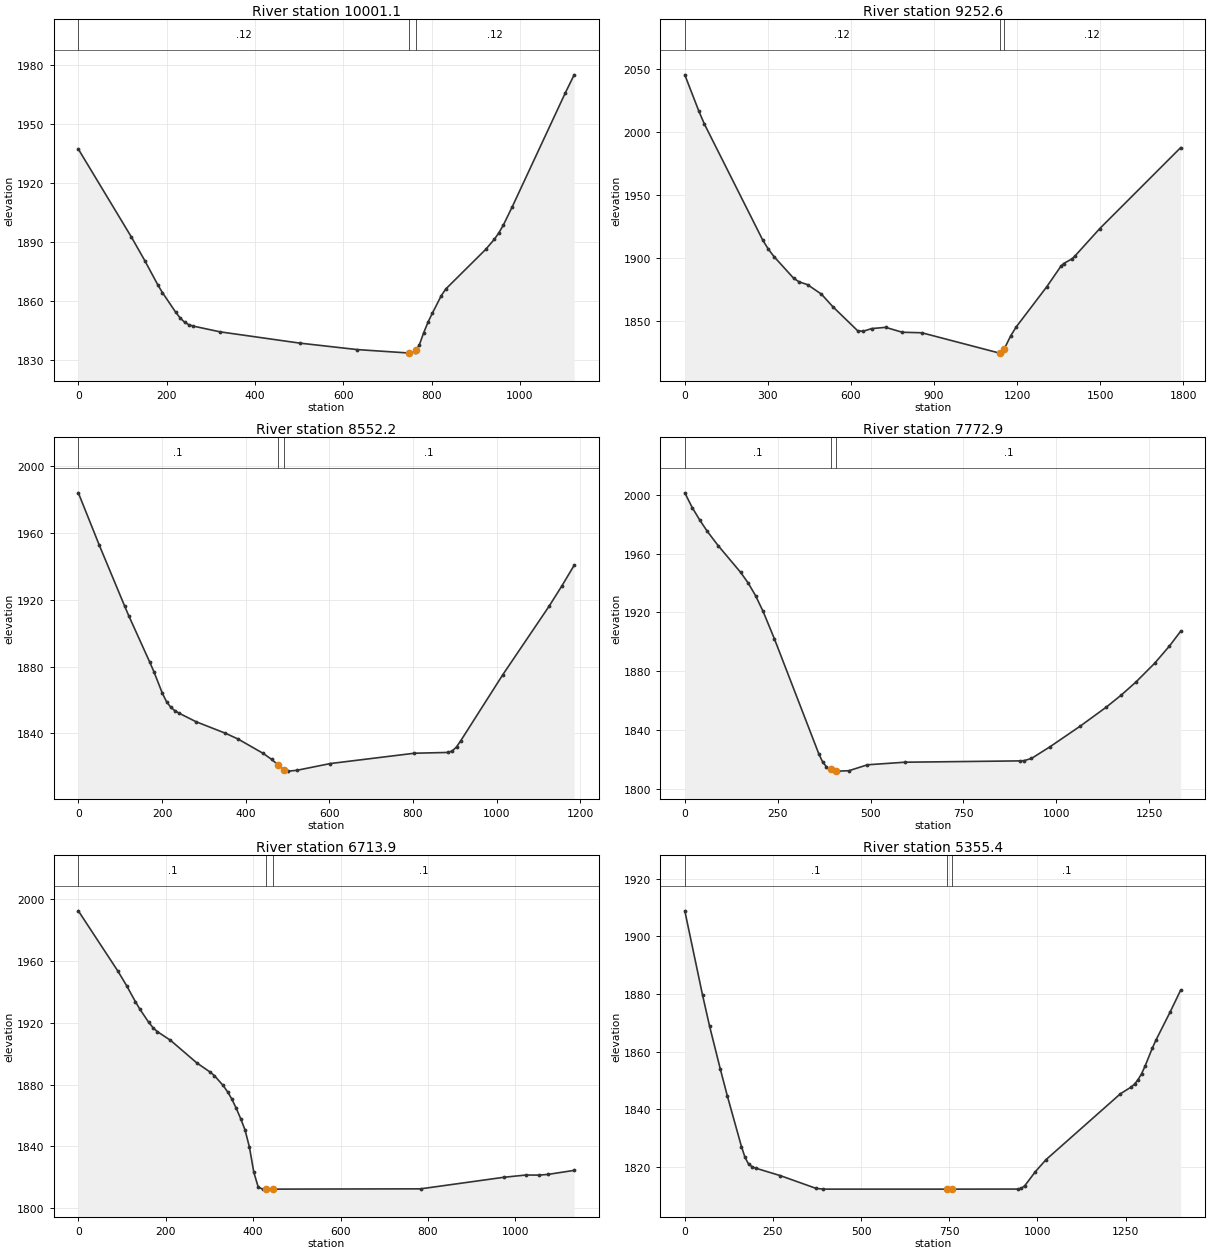
Type RM Length L Ch R = 1 ,10001.1 ,742.8,748.5,754.2
XS GIS Cut Line= 2
     2154602.217      273894.689     2155639.897      273465.173
#Sta/Elev= 30
       0  1937.1   120.3 1892.38   150.4 1880.49   180.5 1867.93   190.5  1864.2
   220.6  1854.2   230.6 1851.33   240.7 1849.14   250.7 1847.84   260.7 1847.15
   320.9 1844.26   501.4 1838.53   631.7 1835.24   749.3 1833.49     752 1833.44
   762.1 1834.13   764.3 1834.86   772.1 1837.43   782.1 1843.66   792.2 1849.26
   802.2 1853.86   822.2 1862.67   832.3 1866.02   922.5 1886.09   942.6 1891.35
   952.6 1894.58   962.6 1898.44   982.7 1907.71    1103 1965.62  1123.1 1974.82
#Mann= 3 , 0 , 0
       0     .12       0   749.3    .045       0   764.3     .12       0
Bank Sta=749.3,764.3
XS Rating Curve= 0 ,0
Exp/Cntr=0.3,0.1

Type RM Length L Ch R = 1 ,9252.6  ,692.6,700.4,708
XS GIS Cut Line= 4
     2154514.793      274772.726     2155005.126      274309.001
     2155719.719      274198.771     2155780.535      273811.067
#Sta/Elev= 30
       0 2045.64    50.4 2016.98    70.5 2006.64     282 1914.06   302.2 1906.93
   322.3 1901.15   392.8 1884.02     413 1881.09   443.2 1878.89   493.6 1871.27
   533.9  1861.5   624.5 1842.18   644.7 1841.88   674.9 1843.96   725.1 1844.94
   785.4 1841.04   855.6 1840.64  1136.8 1824.45  1137.5 1824.52  1146.9 1825.41
  1152.5 1827.34    1177 1838.28  1197.1 1845.39  1307.6 1877.37  1357.8 1893.42
  1367.8 1895.64  1397.9 1899.36    1408 1901.44  1498.6 1923.49  1790.4 1987.75
#Mann= 3 , 0 , 0
       0     .12       0  1137.5    .045       0  1152.5     .12       0
Bank Sta=1137.5,1152.5
XS Rating Curve= 0 ,0
Exp/Cntr=0.3,0.1

Type RM Length L Ch R = 1 ,8552.2  ,779.7,779.3,779.1
XS GIS Cut Line= 2
     2154682.039      274753.721     2155847.201      274970.705
#Sta/Elev= 30
       0 1984.06    50.2 1952.66   110.5 1916.39   120.5 1910.49   170.8 1882.64
   180.8 1876.91   200.9 1864.01   210.9    1859     221 1855.65     231 1853.59
   241.1  1852.1   281.2 1847.05   351.5 1840.14   381.7 1836.68   441.9 1828.07
     462 1824.48   477.3 1821.22   492.3 1818.26   502.2 1817.45   522.3 1817.94
   602.6    1822   803.5 1828.17   883.9 1828.64   893.9 1829.55     904 1831.94
     914 1835.61  1014.4 1875.09  1124.9 1916.04  1155.1 1928.04  1185.2 1940.68
#Mann= 3 , 0 , 0
       0      .1       0   477.3    .045       0   492.3      .1       0
Bank Sta=477.3,492.3
XS Rating Curve= 0 ,0
Exp/Cntr=0.3,0.1

Type RM Length L Ch R = 1 ,7772.9  ,1060.4,1059,1057.4
XS GIS Cut Line= 2
     2154549.003      275521.529     2155864.158       275749.59
#Sta/Elev= 30
       0 2001.25    20.1 1991.19    40.1 1982.83    60.2 1975.22    90.3 1965.25
   150.5 1947.19   170.6 1940.02   190.7 1931.35   210.8 1920.73   240.9 1902.32
   361.3 1823.68   371.3 1818.41   381.4 1815.27   393.3 1813.42   408.3 1812.38
   411.5 1812.28   441.6 1812.55   491.8 1816.58   592.1 1818.33   903.2 1819.24
   913.3  1819.4   933.3 1820.89   983.5 1828.88  1063.8 1842.71  1134.1 1855.63
  1174.2 1863.76  1214.4 1872.76  1264.5 1885.42  1304.7 1897.22  1334.8 1907.22
#Mann= 3 , 0 , 0
       0      .1       0   393.3    .045       0   408.3      .1       0
Bank Sta=393.3,408.3
XS Rating Curve= 0 ,0
Exp/Cntr=0.3,0.1

Type RM Length L Ch R = 1 ,6713.9  ,1356.1,1358.5,1360.5
XS GIS Cut Line= 2
     2154552.189      276555.336     2155681.709      276658.036
#Sta/Elev= 30
       0 1992.45    90.3 1953.51   110.4 1944.04   130.5 1933.67   140.5 1928.89
   160.6 1920.44   170.6 1916.89   180.7 1914.25   210.8 1908.64     271    1894
   301.1 1888.14   311.2 1885.78   331.2 1879.38   341.3 1875.34   351.3 1870.49
   361.3 1864.58   371.4 1857.89   381.4 1850.54   391.4 1839.44   401.5 1823.08
   411.5 1813.63   421.6 1812.28   430.2 1812.28   445.2 1812.28   782.9 1812.46
   973.6 1819.96  1023.8 1821.41  1053.9 1821.36    1074  1821.8  1134.2 1824.42
#Mann= 3 , 0 , 0
       0      .1       0   430.2    .045       0   445.2      .1       0
Bank Sta=430.2,445.2
XS Rating Curve= 0 ,0
Exp/Cntr=0.3,0.1

Type RM Length L Ch R = 1 ,5355.4  ,1165,1163.9,1163.8
XS GIS Cut Line= 2
      2154357.22      277735.303     2155742.525      277976.992
#Sta/Elev= 30
       0 1908.82    50.2 1879.67    70.3 1868.81   100.4 1854.08   120.5 1844.67
   160.7 1827.04   170.8 1823.29   180.8 1820.98   190.8 1820.07   200.9 1819.56
   271.2 1816.95   371.6 1812.57   391.7 1812.28   742.6 1812.28   757.6 1812.28
   944.2  1812.3   954.2 1812.56   964.3 1813.48   994.4 1818.36  1024.5 1822.51
  1235.5 1845.36  1265.6 1847.67  1275.6 1848.72  1285.7  1850.3  1295.7 1852.37
  1305.8 1855.09  1325.9 1861.19  1335.9  1863.9  1376.1 1873.64  1406.2 1881.28
#Mann= 3 , 0 , 0
       0      .1       0   742.6    .045       0   757.6      .1       0
Bank Sta=742.6,757.6
XS Rating Curve= 0 ,0
Exp/Cntr=0.3,0.1

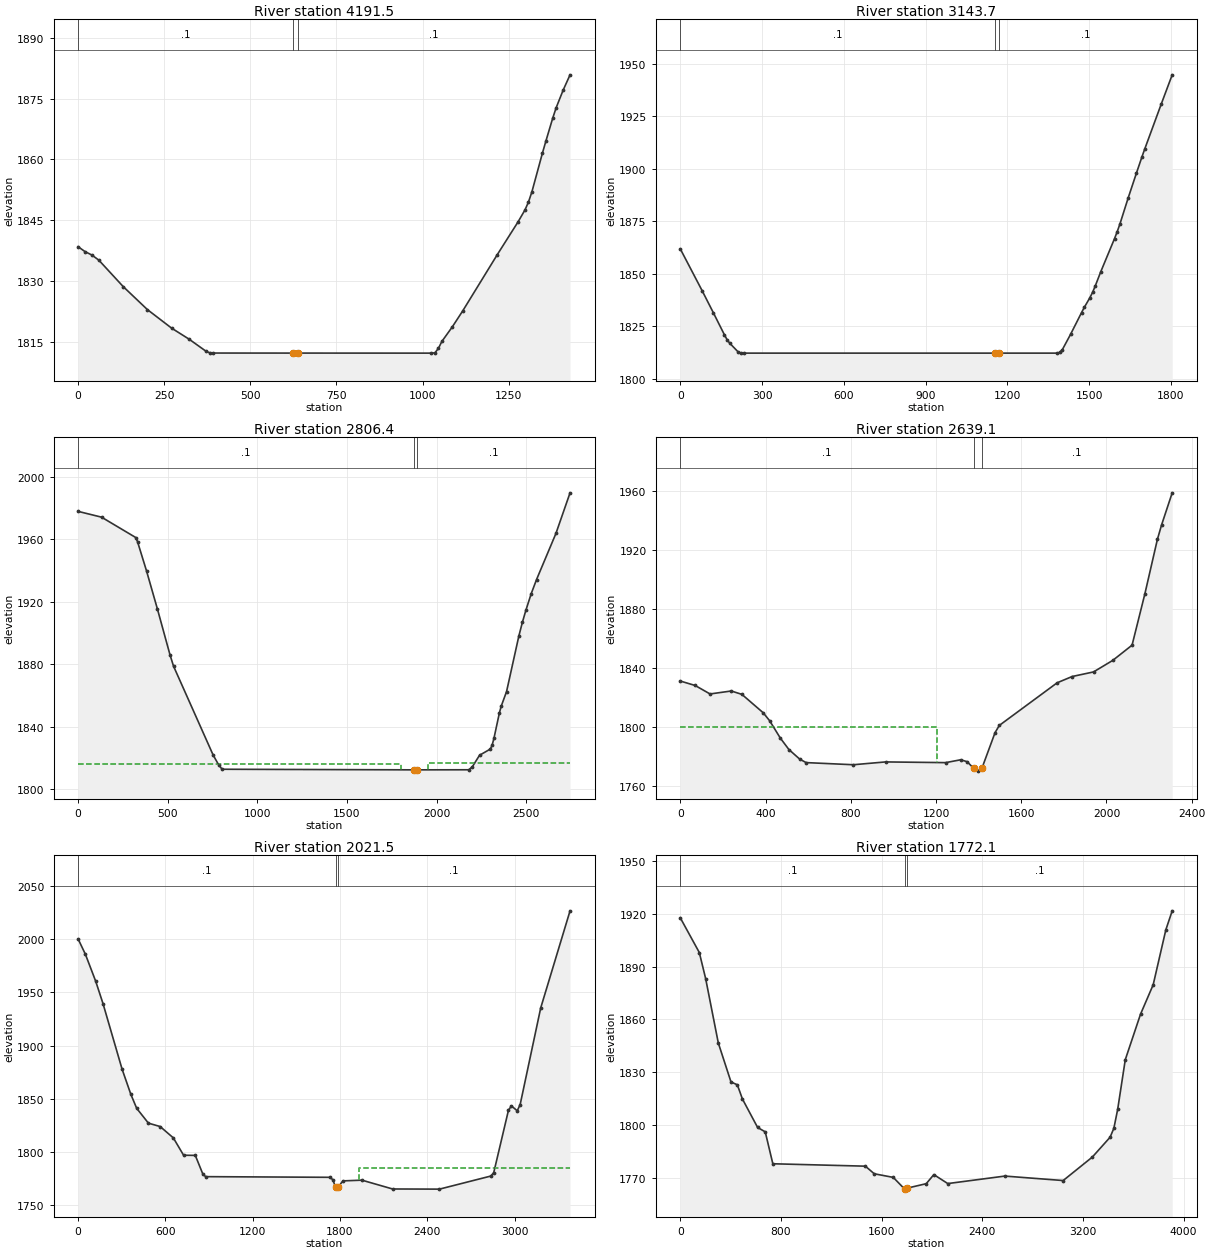
Type RM Length L Ch R = 1 ,4191.5  ,1043.8,1047.9,1051
XS GIS Cut Line= 2
     2154099.474        278817.7      2155507.25       279057.24
#Sta/Elev= 30
       0  1838.5    20.1 1837.29    40.2 1836.44    60.3 1835.17   130.7 1828.68
   201.1    1823   271.5 1818.42   321.8 1815.73   372.1 1812.68   382.1 1812.36
   392.2 1812.29   622.9 1812.28   637.9 1812.28  1025.8 1812.27  1035.8 1812.35
  1045.9 1813.45  1055.9 1815.15  1086.1 1818.73  1116.3 1822.66  1216.8 1836.55
  1277.2 1844.64  1297.3 1847.59  1307.3 1849.51  1317.4 1852.07  1347.6  1861.5
  1357.6 1864.46  1377.7 1870.19  1387.8 1872.78  1407.9 1877.08    1428 1880.87
#Mann= 3 , 0 , 0
       0      .1       0   622.9    .045       0   637.9      .1       0
Bank Sta=622.9,637.9
XS Rating Curve= 0 ,0
Exp/Cntr=0.3,0.1

Type RM Length L Ch R = 1 ,3143.7  ,340.3,337.3,334.2
XS GIS Cut Line= 2
     2153606.348      279478.398     2155351.019      279942.123
#Sta/Elev= 30
       0 1861.88    80.7 1841.85     121 1831.58   161.4 1821.14   171.4 1818.74
   181.5 1816.99   211.8 1812.92   221.9 1812.34     232 1812.28  1154.3 1812.28
  1169.3 1812.28  1381.7 1812.28  1391.8 1812.58  1401.8 1813.87  1432.1 1821.19
  1472.4 1831.53  1482.5 1834.03  1502.7 1838.56  1512.8 1841.13  1522.9 1844.27
    1543    1851  1593.5 1866.76  1603.5  1870.1  1613.6 1873.83  1643.9 1886.23
  1674.1 1897.99  1694.3 1905.72  1704.4  1909.4  1764.9 1930.76  1805.2  1944.7
#Mann= 3 , 0 , 0
       0      .1       0  1154.3    .045       0  1169.3      .1       0
Bank Sta=1154.3,1169.3
XS Rating Curve= 0 ,0
Exp/Cntr=0.3,0.1

Type RM Length L Ch R = 1 ,2806.4  ,170.9,167.3,163.7
XS GIS Cut Line= 4
     2152834.594      279630.125     2153511.508      279960.587
     2155137.166      280157.798      2155467.87      280030.644
#Sta/Elev= 30
       0 1977.96   130.6 1974.26   321.4 1961.21   331.4 1958.55   381.7  1939.8
   441.9 1915.61   512.2 1886.21   532.3 1878.76   753.3 1821.81   783.4 1815.63
   803.5 1812.66  1873.8 1812.28 1880.75 1811.46  1888.8 1812.28  2179.9 1812.33
    2200 1814.26  2240.2 1821.65  2300.4  1825.6  2310.5 1828.16  2320.5 1832.47
  2350.7 1848.67  2360.7 1852.97  2390.8 1862.42  2459.7 1898.17  2479.4 1906.93
  2499.1 1914.71  2528.6 1925.25  2558.2 1934.26  2666.4 1963.81  2745.2 1989.86
#Mann= 3 , 0 , 0
       0      .1       0  1873.8    .045       0  1888.8      .1       0
#XS Ineff= 2 , 0
         1800.54 1815.78 1949.87         1816.82
Permanent Ineff=
       F       F
Bank Sta=1873.8,1888.8
XS Rating Curve= 0 ,0
Exp/Cntr=0.3,0.1

Type RM Length L Ch R = 1 ,2639.1  ,614.3,617.6,620.9
XS GIS Cut Line= 5
     2153213.026      280331.024     2153588.793      280283.054
     2154777.389      280253.739     2155329.047      280277.724
     2155462.298      280144.473
#Sta/Elev= 30
       0 1830.91    69.8 1827.89   139.6 1822.15   239.2 1824.16   289.1 1821.87
   388.9 1809.42   419.1 1804.04   469.5 1792.22   509.8 1784.46   560.2 1778.01
   590.4 1775.62   812.1 1774.17   963.2 1776.08  1245.4  1775.6  1315.9 1777.54
  1346.1 1776.23  1376.3 1771.82  1396.5 1769.84  1416.6 1772.24  1477.1 1795.94
  1497.2 1800.84  1768.6 1829.73  1838.8 1833.97  1939.2 1837.08  2029.6 1844.92
    2120 1855.22  2179.5 1889.61    2239 1926.99  2258.8 1936.85  2308.4 1958.49
#Mann= 3 , 0 , 0
       0      .1       0  1376.3    .045       0  1416.6      .1       0
#XS Ineff= 2 , 0
          1203.4 1799.45
Permanent Ineff=
       F       F
Bank Sta=1376.3,1416.6
XS Rating Curve= 0 ,0
Exp/Cntr=0.3,0.1

Type RM Length L Ch R = 1 ,2021.5  ,263.2,249.4,248.3
XS GIS Cut Line= 4
     2152796.096      280135.342       2153921.2       280784.05
     2154868.922      280885.411     2155639.264      280059.321
#Sta/Elev= 30
       0 1999.95    50.3  1985.5   120.8 1960.27   171.2 1939.22     302 1877.85
   362.4 1854.12   402.7 1840.99   483.2 1827.12   563.8 1823.95   654.4  1813.3
   724.9 1797.02   805.4 1796.87   855.8 1779.84   875.9 1776.92  1730.1  1776.3
  1750.2 1774.17  1769.8 1767.04  1784.8 1766.82  1820.4 1772.94  1950.9 1773.62
  2161.6 1765.35  2483.8 1765.21  2836.8 1777.48    2857 1780.78  2957.8 1839.08
    2978 1843.36  3018.3 1838.72  3038.5 1844.59  3179.7 1935.24  3381.4 2026.39
#Mann= 3 , 0 , 0
       0      .1       0  1769.8    .045       0  1784.8      .1       0
#XS Ineff= 2 , 0
                         1931.98         1784.64
Permanent Ineff=
       F       F
Bank Sta=1769.8,1784.8
XS Rating Curve= 0 ,0
Exp/Cntr=0.3,0.1

Type RM Length L Ch R = 1 ,1772.1  ,1753.9,1772.1,1777.6
XS GIS Cut Line= 4
     2152737.144      280331.412     2154096.469      281057.976
     2155130.652      281143.247     2155985.548      280124.369
#Sta/Elev= 30
       0  1917.7   151.1 1897.98   201.5 1883.14   302.2  1846.5     403 1824.38
   453.3 1822.76   493.6 1814.72   614.5  1798.5     675 1796.02   735.4 1777.87
  1470.8  1776.5  1541.3 1772.18  1692.4 1770.12  1783.1 1763.45  1785.1  1763.5
  1800.1 1763.96  1954.4 1766.55  2014.8  1771.7  2125.6 1766.61    2579 1770.87
  3042.5 1768.33  3274.2 1781.67  3415.3 1792.94  3445.5 1798.06  3475.8 1808.85
  3536.2 1837.06  3657.1 1862.88  3757.9 1879.65  3858.6 1910.93    3909 1921.68
#Mann= 3 , 0 , 0
       0      .1       0  1785.1    .045       0  1800.1      .1       0
Bank Sta=1785.1,1800.1
XS Rating Curve= 0 ,0
Exp/Cntr=0.3,0.1

Chan Stop Cuts=-1
Use User Specified Reach Order=0